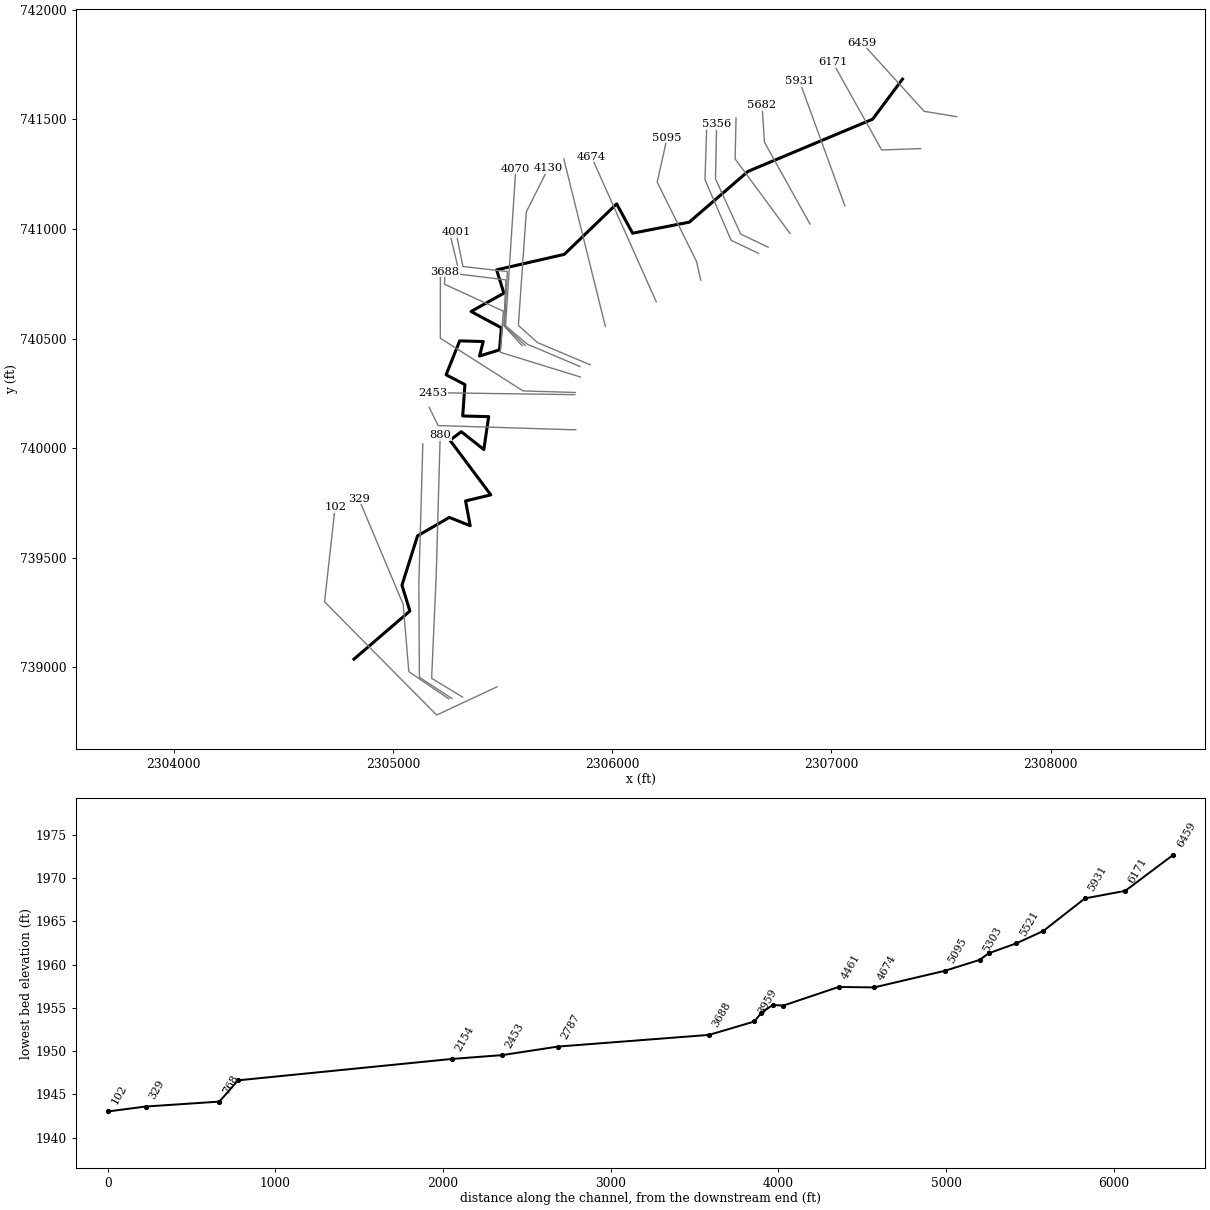
--- WLMTHRN.prj (project) ---

Proj Title=WLMTHRN
Current Plan=p01
Default Exp/Contr=0,0
English Units
Geom File=g01
Flow File=f01
Plan File=p01
BEGIN DESCRIPTION:
----------MODEL BY WOOD PLC 2022----------
AFH study
Randolph County, WV
HEC-RAS Version: RAS 6.2
Vertical Datum: NAVD88
Projection: NAD 1983 StatePlane West Virginia S FIPS 4702 (US Feet)
Terrain: 1-meter LIDAR (FEMA Region III 3DEP collected 2016-2018)
Land Use: 2019 NLCD
Hydrologic Method:
WV SIR2010-5033 regression equations
Additional Model Notes:
None
END DESCRIPTION:
DSS Export Rating Curves= 0
DSS Export Rating Curve Sorted= 0
DSS Export Volume Flow Curves= 0
DXF OffsetX= 0
DXF OffsetY= 0
DXF ScaleX= 0
DXF ScaleY= 0

--- WLMTHRN.p01 (plan) ---

Plan Title=Floodplain
Program Version=6.20
Short Identifier=Floodplain
Geom File=g01
Flow File=f01
Subcritical Flow
K Sum by GR= 0
Std Step Tol= 0.01
Critical Tol= 0.01
Num of Std Step Trials= 20
Max Error Tol= 0.3
Flow Tol Ratio= 0.001
Split Flow NTrial= 30
Split Flow Tol= 0.02
Split Flow Ratio= 0.02
Log Output Level= 0
Friction Slope Method= 1
Unsteady Friction Slope Method= 2
Unsteady Bridges Friction Slope Method= 1
Parabolic Critical Depth
Global Vel Dist= 0 , 0 , 0
Global Log Level= 0
CheckData=True
Encroach Param=-1 ,0,0, 0
Mapping Interval=1HOUR
Computation Time Step Use Courant=        0
Computation Time Step Use Time Series=    0
Computation Time Step Count To Double=0
Computation Time Step Max Doubling=0
Computation Time Step Max Halving=0
Computation Time Step Residence Courant=0
Run HTab= 0
Run UNet= 0
Run Sediment= 0
Run PostProcess= 0
Run WQNet= 0
Run RASMapper= 0
UNET Theta= 0
UNET Theta Warmup= 0
UNET ZTol= 0
UNET ZSATol= 0
UNET MxIter= 0
UNET Max Iter WO Improvement= 0
UNET MaxInSteps= 0
UNET DtIC= 0
UNET DtMin= 0
UNET MaxCRTS= 0
UNET WFStab= 0
UNET SFStab= 0
UNET WFX= 1
UNET SFX= 1
UNET Gravity=32.174
UNET 1D Methodology=Finite Difference
UNET DSS MLevel= 1
UNET Pardiso=0
UNET DZMax Abort= 0
UNET Use Existing IB Tables= 0
UNET Froude Reduction=False
UNET Froude Limit= 0
UNET Froude Power= 0
UNET D1 Cores= 0
UNET WindReference=Eulerian
UNET WindDragFormulation=Hsu (1988)
UNET D2 Coriolis=0
UNET D2 Cores= 0
UNET D2 Theta= 1
UNET D2 Theta Warmup= 1
UNET D2 Z Tol= 0.01
UNET D2 Volume Tol= 0.01
UNET D2 Max Iterations= 20
UNET D2 Equation= 0
UNET D2 RampUpFraction=0.1
UNET D2 TimeSlices= 1
UNET D2 Turbulence Formulation=Non-Conservative (original)
UNET D2 Eddy Viscosity=0.3
UNET D2 Transverse Eddy Viscosity=0.1
UNET D2 Smagorinsky Mixing=0
UNET D2 BCVolumeCheck=0
UNET D2 Cores=0
UNET D2 SolverType=PARDISO (Direct)
UNET D2 Minimum Iterations= 2147483647
UNET D2 Maximum Iterations= 2147483647
UNET D2 Restart Number= 10
UNET D2 Relaxation Coeff=1.3
UNET D2 SOR Precondition Iterations= 10
UNET D2 ILUT Maximum Fill= 8
UNET D2 ILUT Tolerance=1E-08
UNET D1D2 MaxIter= 0
UNET D1D2 ZTol=0.01
UNET D1D2 QTol=0.1
UNET D1D2 MinQTol=1
Write IC File= 0
Write IC File at Fixed DateTime=0
Write IC File at Sim End=0
Echo Input=False
Echo Parameters=False
Echo Output=False
Write Detailed= 0
HDF Write Warmup=0
HDF Write Time Slices=0
HDF Flush=0
HDF Compression= 1
HDF Chunk Size= 1
HDF Spatial Parts= 1
HDF Use Max Rows=0
HDF Fixed Rows= 1
Calibration Method= 0
Calibration Iterations= 20
Calibration Max Change=0.05
Calibration Tolerance=0.2
Calibration Maximum=1.5
Calibration Minimum=0.5
Calibration Optimization Method= 1
WQ AD Non Conservative
WQ ULTIMATE=-1
WQ Max Comp Step=1HOUR
WQ Output Interval=15MIN
WQ Output Selected Increments= 0
WQ Output face flow=0
WQ Output face velocity=0
WQ Output face area=0
WQ Output face dispersion=0
WQ Output cell volume=0
WQ Output cell surface area=0
WQ Output cell continuity=0
WQ Output cumulative cell continuity=0
WQ Output face conc=0
WQ Output face dconc_dx=0
WQ Output face courant=0
WQ Output face peclet=0
WQ Output face adv mass=0
WQ Output face disp mass=0
WQ Output cell mass=0
WQ Output cell source sink temp=0
WQ Output nsm pathways=0
WQ Output nsm derived pathways=0
WQ Create Restart=0
WQ Fixed Restart=0
WQ System Summary=0
WQ Write To DSS=0
Sorting and Armoring Iterations= 10
XS Update Threshold= 0.02
Bed Roughness Predictor= 0
Hydraulics Update Threshold= 0.02
Energy Slope Method= 1
Volume Change Method= 1
Sediment Retention Method= 0
Sediment TS Multiplier= 1
Warm Up Method= 0
XS Weighting Method= 0
Number of US Weighted Cross Sections= 1
Number of DS Weighted Cross Sections= 1
Upstream XS Weight=0
Main XS Weight=1
Downstream XS Weight=0
Number of DS XS's Weighted with US Boundary= 1
Upstream Boundary Weight= 1
Weight of XSs Associated with US Boundary= 0
Number of US XS's Weighted with DS Boundary= 1
Downstream Boundary Weight= 0.5
Weight of XSs Associated with DS Boundary= 0.5
Percentile Method= 0
Sediment Output Level= 3
Mass or Volume Output= 0
Output Increment Type= 1
Profile and TS Output Increment= 1
Transport Output Increment 1
XS Output Flag= 0
XS Output Increment= 10
Read HDF5 Sediment Hotstart= 0
Sediment Hotstart Type= 0
Write Gradation File= 0
Read Gradation Hotstart= 0
Write HDF5 File= 1
Write Binary Output= 1
Write DSS Sediment File= 0
DSS Sediment Output Type= 1
SV Curve= 0
Specific Gage Flag= 0
Subcell Erosion Methods= 0
Subcell Deposition Methods= 0
Advection Scheme= 1
Matrix Solver= 0
Implicit Weighting Factor= 1
Maximum Outer Loop Convergence Iterations= 5
Convergence Maximum Absolute= 0.001
Convergence RMSE= 0.0001
Grain Fractions Max Abs Error= 0.001
Max Subgrid Regions= 1
Max Subgrid Length Scale= 3.402823E+38
Initial Layer Thickness= 3.402823E+38
Min Layer Thickness= 3.402823E+38
Max Layer Thickness= 3.402823E+38
Number of Layers= 5

--- WLMTHRN.f01 (steady flow) ---

Flow Title=Flow
Program Version=6.20
Number of Profiles= 1
Profile Names=P100yr
River Rch & RM=WLMTHRN,Main,6459
     279
River Rch & RM=WLMTHRN,Main,880
     314
Boundary for River Rch & Prof#=WLMTHRN,Main            , 1
Up Type= 0
Dn Type= 3
Dn Slope=0.0029
DSS Import GetInterval= 0
DSS Import GetPeak= 0
DSS Import FillOption= 0

--- WLMTHRN.g01 (geometry) ---

Geom Title=Geometry
Program Version=6.20

River Reach=WLMTHRN         ,Main
Reach XY= 30
     2307323.927       741682.71     2307187.914      741500.328
     2306619.508      741262.191     2306351.492      741030.586
     2306093.235      740980.286     2306020.412      741113.919
     2305781.675      740883.815     2305472.984      740813.113
     2305506.104      740706.768     2305356.376      740623.306
     2305494.889      740548.982     2305486.056       740448.23
     2305395.144      740420.225     2305411.863      740486.284
     2305304.575      740489.297     2305242.638      740334.643
2305328.39469068 740290.13059748     2305318.381      740146.834
2305436.83183476 740143.69276272     2305414.666      739993.812
     2305311.964      740075.161     2305260.281      740036.221
     2305446.582      739787.148     2305331.449      739759.443
     2305352.491      739646.314     2305257.529      739684.344
     2305112.391      739600.316     2305041.297      739375.316
     2305077.495      739257.347     2304822.464      739038.058

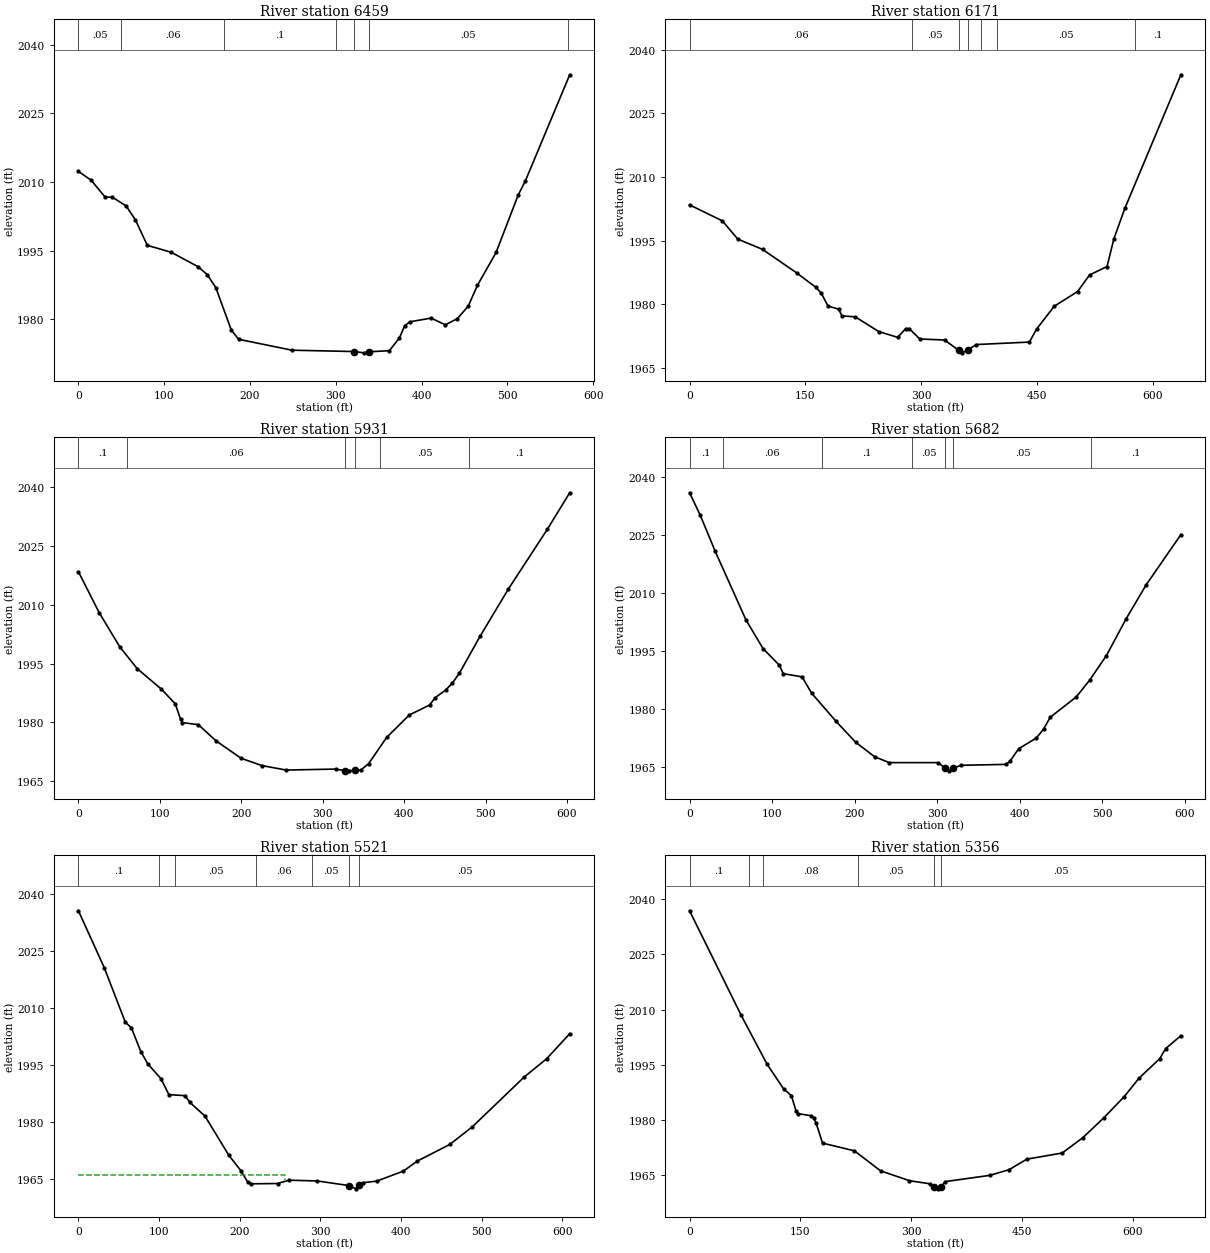
Type RM Length L Ch R = 1 ,6459    ,287.6,287.6,287.6
XS GIS Cut Line= 3
 2307570.9268219741511.5135836752307422.90109006741536.106720049
 2307138.7004763741848.712112974
#Sta/Elev= 30
       0 2012.34      15 2010.38    31.2  2006.7    39.3 2006.71    55.5 2004.81
    66.4 2001.75    80.3 1996.18   108.2 1994.66   139.4 1991.52   150.1  1989.8
   160.1 1986.95   178.2 1977.65   186.7 1975.66   248.8 1973.28  321.65 1972.98
   332.5  1972.7   338.4 1972.94   362.3 1973.16   374.1 1975.97   380.1 1978.58
     386 1979.47     411 1980.29   427.6 1978.82   441.6 1980.18   454.2 1982.88
     465 1987.46   486.7 1994.62   512.4 2007.14   520.9 2010.29   572.5 2033.44
#Mann= 7, -1 ,  0
       0    0.05       0      50    0.06       0  170.05     0.1       0
  300.05    0.05       0  321.65   0.045       0   338.4    0.05       0
  570.05    0.12       0
Bank Sta=321.65,338.4
XS Rating Curve= 0 ,0
Exp/Cntr(USF)=0,0
Exp/Cntr=0.3,0.1

Type RM Length L Ch R = 1 ,6171    ,240.2,240.2,240.2
XS GIS Cut Line= 3
2307406.64428065741366.0430515732307229.04226199  741359.8714218
2307005.36946663741760.407698412
#Sta/Elev= 30
       0 2003.44    42.5 1999.66    62.5 1995.35    94.5 1992.94   138.6  1987.4
   163.4 1984.01   170.6 1982.62   179.3 1979.57     193 1978.83   197.5 1977.24
   214.6 1977.02   245.1 1973.54   269.7 1972.17     280 1974.25   284.6 1974.23
   298.3 1971.79   330.4 1971.55348.43131969.145   353.3 1968.52360.59121969.229
   371.6 1970.48   440.3 1971.06   449.5  1974.1   472.4 1979.51   502.7 1982.98
   518.2 1986.89   540.9 1988.89   549.7  1995.4     564 2002.64   636.5 2034.13
#Mann= 7, -1 ,  0
       0    0.06       0  287.71    0.05       0348.4313   0.045       0
360.5912    0.05       0  377.71     0.1       0  397.71    0.05       0
  577.71     0.1       0
Bank Sta=348.4313,360.5912
XS Rating Curve= 0 ,0
Exp/Cntr(USF)=0,0
Exp/Cntr=0.3,0.1

Type RM Length L Ch R = 1 ,5931    ,248.5,248.5,248.5
XS GIS Cut Line= 2
2307061.09196102741105.3799656082306854.82198671741672.473835054
#Sta/Elev= 30
       0 2018.46    25.5 2008.02    50.9 1999.26    72.1 1993.75   101.9  1988.5
     119 1984.74   125.4 1980.81   127.5 1979.96   147.3 1979.43   169.1 1975.29
   199.8 1970.86   225.4 1968.99   255.2 1967.85   315.8  1968.1327.96811967.688
   331.8 1967.65339.36821967.751     347 1967.87   356.4 1969.47   378.6 1976.19
   406.3 1981.89   431.3 1984.45   438.2 1986.33     451 1988.26   459.4 1990.08
     468  1992.6   493.5 2002.06     528 2014.02   576.1 2029.35   603.4 2038.61
#Mann= 6, -1 ,  0
       0     0.1       0      60    0.06       0327.9681   0.045       0
339.3682    0.06       0     370    0.05       0     480     0.1       0
Bank Sta=327.9681,339.3682
XS Rating Curve= 0 ,0
Exp/Cntr(USF)=0,0
Exp/Cntr=0.3,0.1

Type RM Length L Ch R = 1 ,5682    ,161.3,161.3,161.3
XS GIS Cut Line= 4
2306902.07313304 741022.00224179 2306694.4618573 741395.11848145
2306685.87704645741526.4624894292306683.19672268741563.161673442
#Sta/Elev= 30
       0 2035.86    12.8 2030.12    31.1  2020.7    68.4 2002.93      89 1995.54
   108.9  1991.2   113.5 1989.04   136.4  1988.2   147.8 1984.02   177.6 1976.67
   201.3 1971.28   224.3 1967.52     242 1966.01   301.2 1966.01309.39361964.667
   314.9 1963.88319.79351964.555   328.6 1965.31   383.1 1965.55   388.1  1966.3
   398.8 1969.59   420.2 1972.37   429.1 1974.69   437.1 1977.75   468.7 1983.02
   485.2 1987.45   505.2 1993.72   528.9 2003.17   553.3 2012.01   595.4 2025.01
#Mann= 7, -1 ,  0
       0     0.1       0      40    0.06       0     160     0.1       0
     270    0.05       0309.3936   0.045       0319.7935    0.05       0
  486.99     0.1       0
Bank Sta=309.3936,319.7935
XS Rating Curve= 0 ,0
Exp/Cntr(USF)=0,0
Exp/Cntr=0.3,0.1

Type RM Length L Ch R = 1 ,5521    ,164.7,164.7,164.7
BEGIN DESCRIPTION:
Structure XS 4
END DESCRIPTION:
XS GIS Cut Line= 3
2306811.12858333740978.8347767242306560.81675613741318.749852209
2306564.83213603741505.919144858
#Sta/Elev= 30
       0 2035.59      32 2020.65    58.1 2006.31    65.7  2004.8    77.4 1998.56
    85.9 1995.36   102.3 1991.44   112.2 1987.23   132.1 1986.96   138.2  1985.2
   156.9  1981.6   186.7 1971.22   201.6  1967.2   209.8 1964.28   214.1 1963.77
     247 1963.85   261.2 1964.72     296 1964.53335.76461963.305   344.2 1962.45
348.44431963.403   352.8 1964.06     370 1964.48     403 1967.12   420.2 1969.74
   460.6 1974.13   488.6 1978.78   553.1 1991.91   580.6 1996.65   609.3 2003.25
#Mann= 7, -1 ,  0
       0     0.1       0     100    0.06       0     120    0.05       0
     220    0.06       0     290    0.05       0335.7646   0.045       0
348.4443    0.05       0
#XS Ineff= 2 , 0
          255.74 1966.21
Permanent Ineff=
       T       F
Bank Sta=335.7646,348.4443
XS Rating Curve= 0 ,0
Exp/Cntr(USF)=0,0
Exp/Cntr=0.3,0.1

Type RM Length L Ch R = 1 ,5356    ,53.5,53.5,53.5
BEGIN DESCRIPTION:
Structure XS 3
END DESCRIPTION:
XS GIS Cut Line= 4
2306711.32655368740916.4902124832306586.19330749740976.300210965
2306471.07277294741228.0669809612306476.37628753741477.759203686
#Sta/Elev= 30
       0 2036.85      70 2008.41   104.9 1995.19   127.6 1988.39   137.9 1986.64
   144.1 1982.51   146.9 1981.73     165 1981.16     168 1980.49   171.1 1979.32
   180.1 1973.72   223.2 1971.63   258.6  1966.2   297.8 1963.51     325 1962.69
   330.9 1961.89   335.9  1961.3   340.1 1961.85   346.4 1963.27   406.5 1964.96
   432.6  1966.5   456.7 1969.36   504.7 1971.04   532.7 1975.22   560.7 1980.55
   588.7 1986.37   608.7 1991.38   636.7 1996.67   644.7 1999.41   665.3  2002.9
#Mann= 6, -1 ,  0
       0     0.1       0      80    0.06       0     100    0.08       0
  228.69    0.05       0   330.9   0.045       0   340.1    0.05       0
Bank Sta=330.9,340.1
XS Rating Curve= 0 ,0
Exp/Cntr(USF)=0,0
Exp/Cntr=0.3,0.1

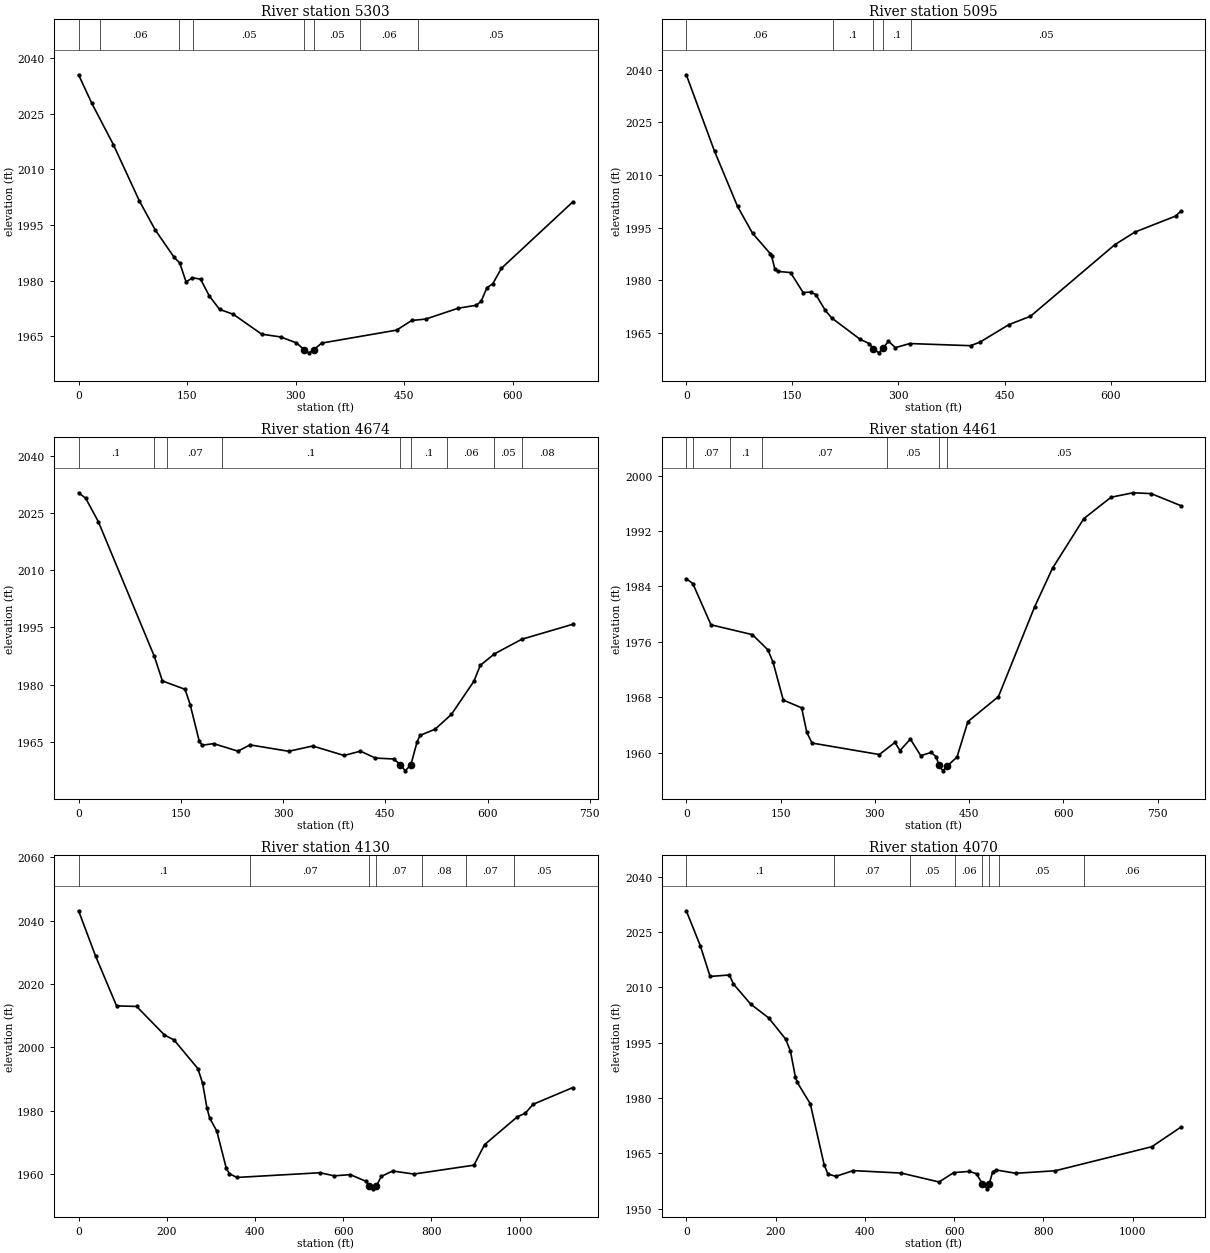
Type RM Length L Ch R = 1 ,5303    ,207.7,207.7,207.7
BEGIN DESCRIPTION:
Structure XS 2
END DESCRIPTION:
XS GIS Cut Line= 4
2306667.59759435740888.3152476082306542.46434816 740948.12524609
2306423.34234101741223.9008516832306431.04673916741467.991012768
#Sta/Elev= 30
       0 2035.53    18.2 2027.88    48.1 2016.69    84.2 2001.45   105.8 1993.73
   132.2 1986.26   139.8  1984.8   148.6 1979.64   157.3  1980.8   168.6  1980.4
   180.8 1975.84   194.9 1972.26   213.9 1970.93   253.1 1965.57   279.3 1964.83
   301.1 1963.22   311.6 1961.43   318.5 1960.54  325.191961.421   336.1 1963.17
   439.6 1966.67   460.4 1969.27   479.9 1969.65   524.4 1972.56   549.8 1973.38
   556.4 1974.46   564.4  1978.1   572.4 1979.15   584.4 1983.34   683.3 2001.29
#Mann= 8, -1 ,  0
       0     0.1       0      30    0.06       0  138.69    0.07       0
  158.69    0.05       0   311.6   0.045       0  325.19    0.05       0
  388.69    0.06       0   469.1    0.05       0
Bank Sta=311.6,325.19
XS Rating Curve= 0 ,0
Exp/Cntr(USF)=0,0
Exp/Cntr=0.3,0.1

Type RM Length L Ch R = 1 ,5095    ,421.3,421.3,421.3
BEGIN DESCRIPTION:
Structure XS 1
END DESCRIPTION:
XS GIS Cut Line= 4
2306403.89432397740766.1639394982306384.58145788 740851.72631185
2306205.40890466741213.008673259 2306250.5797975741416.129131136
#Sta/Elev= 30
       0 2038.59      40 2016.74    72.5 2001.03    93.8 1993.35   118.9 1987.54
   120.6  1986.9   125.1 1983.31   129.5 1982.52   147.4 1982.17   165.2 1976.49
   175.7  1976.6   183.1 1975.91   196.5 1971.41   205.4 1969.26   245.6 1963.17
     259 1961.89264.00781960.491   272.4 1959.28278.1577 1960.54   285.8  1962.6
   295.7 1960.76   315.9 1961.93   401.9 1961.32   415.3 1962.33   456.2 1967.33
   486.7 1969.71   605.9 1990.12   634.2 1993.71   691.9 1998.29   699.1 1999.65
#Mann= 5, -1 ,  0
       0    0.06       0  207.71     0.1       0264.0078   0.045       0
278.1577     0.1       0  317.71    0.05       0
Bank Sta=264.0078,278.1577
XS Rating Curve= 0 ,0
Exp/Cntr(USF)=0,0
Exp/Cntr=0.3,0.1

Type RM Length L Ch R = 1 ,4674    ,212.4,212.4,212.4
XS GIS Cut Line= 2
2306201.02750833740667.6991438872305905.16427635741329.776801412
#Sta/Elev= 30
       0  2030.3    10.4 2028.88      29 2022.71   111.2 1987.36   122.9 1980.95
   156.2 1978.74   163.7 1974.73   176.9  1965.2   181.3 1964.09   198.2 1964.49
   233.8 1962.52   251.4 1964.17   308.3 1962.49   343.4 1963.88   389.4 1961.39
   413.5 1962.52   435.4 1960.71     462 1960.47 472.091 1958.99   479.2 1957.36
487.45241958.985   496.7 1965.05   501.1 1966.67     523 1968.29   546.8 1972.15
   579.9 1980.86   589.2 1985.03     610 1988.04     650 1991.87   725.2 1995.82
#Mann= 9, -1 ,  0
       0     0.1       0     110    0.06       0     130    0.07       0
     210     0.1       0 472.091   0.045       0487.4524     0.1       0
     540    0.06       0     610    0.05       0     650    0.08       0
Bank Sta=472.091,487.4524
XS Rating Curve= 0 ,0
Exp/Cntr(USF)=0,0
Exp/Cntr=0.3,0.1

Type RM Length L Ch R = 1 ,4461    ,331,331,331
BEGIN DESCRIPTION:
Structure XS 3
END DESCRIPTION:
XS GIS Cut Line= 2
2305968.95987951740555.0635597982305779.50693389741318.749852209
#Sta/Elev= 30
       0 1985.13    10.4 1984.41    39.3 1978.47   105.2 1977.05   129.9 1974.86
   138.2 1973.04   154.3 1967.62   183.5  1966.5   191.8 1962.96     200 1961.42
   307.2 1959.76   331.9  1961.5   340.1 1960.34   356.6 1961.99   373.1  1959.6
   389.6 1960.06   397.8 1959.44401.9859 1958.19   408.5 1957.41415.18591958.096
   430.8  1959.4   448.2 1964.52   496.7 1968.11   554.4 1981.07   582.8 1986.63
   632.7 1993.79     676 1996.87     711 1997.51   739.9 1997.39   786.8 1995.66
#Mann= 7, -1 ,  0
       0     0.1       0      10    0.07       0      70     0.1       0
     120    0.07       0     320    0.05       0401.9859   0.045       0
415.1859    0.05       0
Bank Sta=401.9859,415.1859
XS Rating Curve= 0 ,0
Exp/Cntr(USF)=0,0
Exp/Cntr=0.3,0.1

Type RM Length L Ch R = 1 ,4130    ,60.7,60.7,60.7
BEGIN DESCRIPTION:
Structure XS 3
END DESCRIPTION:
XS GIS Cut Line= 5
2305899.52699138740380.2254665492305659.32249902740481.754618838
2305572.18304245740559.8684413822305608.36722245741077.717645359
2305709.15197506741277.540476047
#Sta/Elev= 30
       0 2043.12    38.4 2028.86    86.1 2013.07   131.5 2012.89   194.7 2003.87
   216.4 2002.29   270.4 1993.26   281.1 1988.64   290.9 1980.87   297.2 1977.61
   313.4 1973.48   334.8 1961.75   341.9 1960.03   358.9 1958.85   547.4 1960.34
   579.6 1959.36   615.7 1959.74   651.8 1957.61   659.4 1956.25   667.8 1955.25
   675.1 1956.23   686.4 1959.19   711.9 1960.89     760 1959.92   896.2 1962.73
   920.2 1969.19   994.2 1977.98  1012.5 1979.16  1030.7 1981.99  1120.7 1987.27
#Mann= 7, -1 ,  0
       0     0.1       0  387.81    0.07       0   659.4   0.045       0
   675.1    0.07       0  777.81    0.08       0  877.81    0.07       0
  986.92    0.05       0
Bank Sta=659.4,675.1
XS Rating Curve= 0 ,0
Exp/Cntr(USF)=0,0
Exp/Cntr=0.3,0.1

Type RM Length L Ch R = 1 ,4070    ,69,69,69
BEGIN DESCRIPTION:
Structure XS 2
END DESCRIPTION:
XS GIS Cut Line= 4
2305853.24077838740372.5196923192305613.03628602740474.048844608
2305513.69907728740558.2615432372305560.40464382741273.494027469
#Sta/Elev= 30
       0 2030.81    31.6 2021.24    53.3 2012.99    96.7 2013.38   105.4 2010.96
   144.5 2005.45   184.5 2001.75   222.6 1995.98   233.3 1992.75   244.3  1985.8
   248.7 1984.25   277.8 1978.42     309 1961.82   317.5 1959.34   335.3 1958.74
   374.3 1960.29   482.1 1959.61   566.3  1957.2   599.3 1959.75   634.4 1960.07
   650.5 1959.43   663.2 1956.72   674.5 1955.34   678.8 1956.73   686.6 1959.98
   694.6 1960.45   738.5 1959.56   826.9 1960.25  1043.3 1966.78  1107.8 1972.06
#Mann= 8, -1 ,  0
       0     0.1       0  330.78    0.07       0  501.01    0.05       0
  601.01    0.06       0   663.2   0.045       0   678.8    0.06       0
  701.01    0.05       0  891.01    0.06       0
Bank Sta=663.2,678.8
XS Rating Curve= 0 ,0
Exp/Cntr(USF)=0,0
Exp/Cntr=0.3,0.1

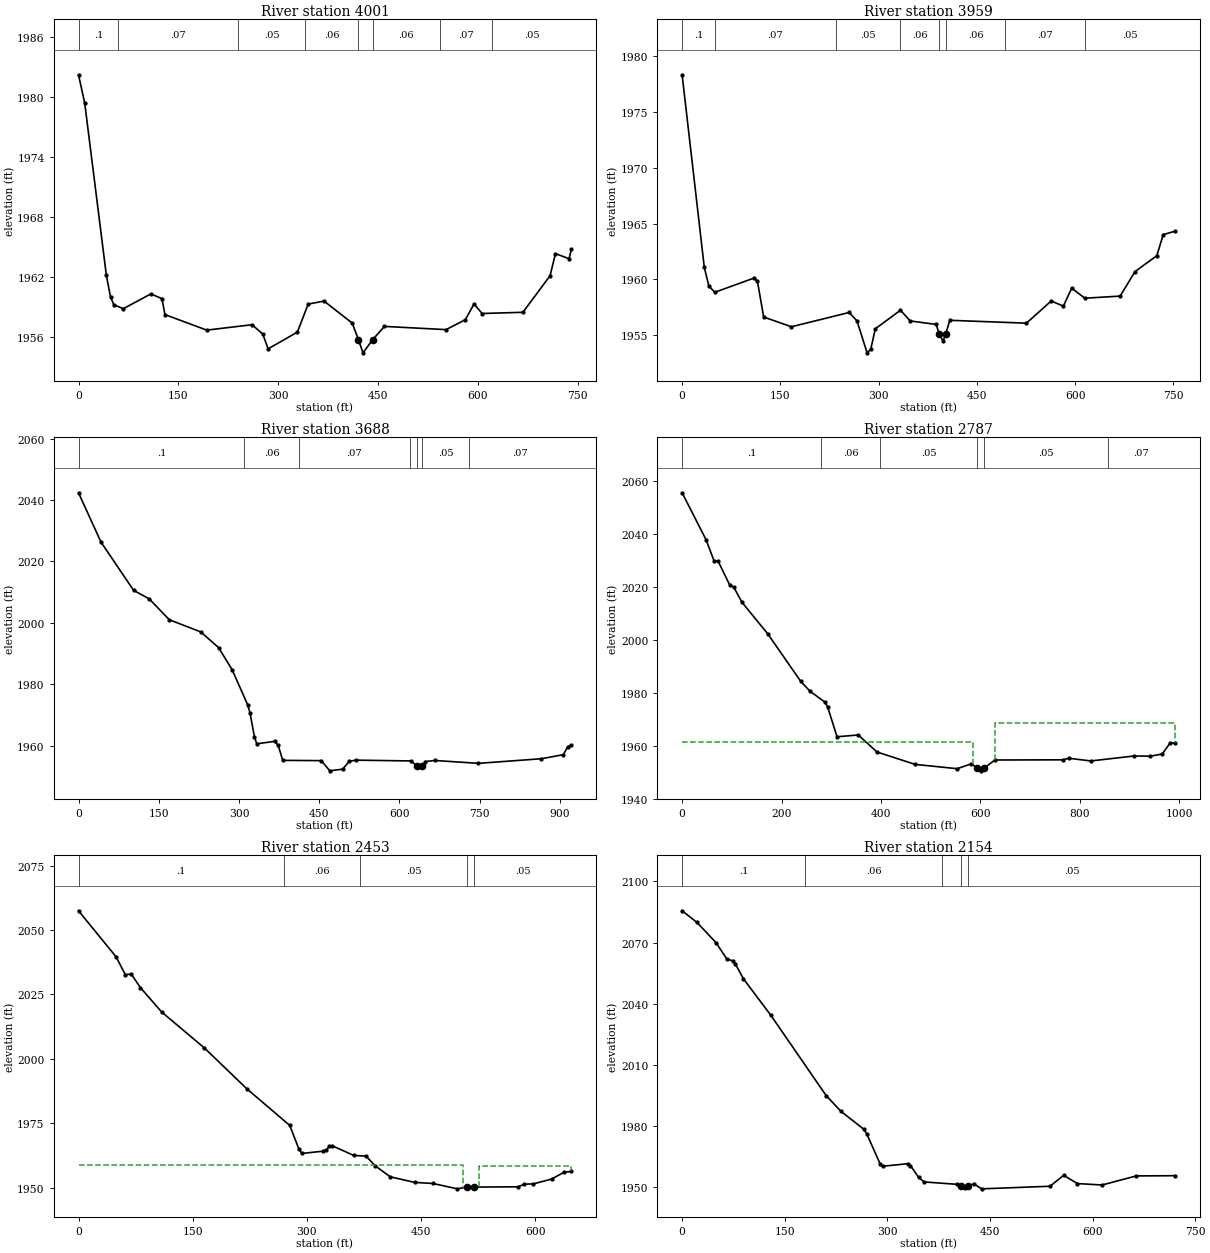
Type RM Length L Ch R = 1 ,4001    ,41.4,41.4,41.4
BEGIN DESCRIPTION:
Structure XS 3
END DESCRIPTION:
XS GIS Cut Line= 6
2305603.01329031740468.8740042812305508.90240201740558.443394188
 2305522.0621288 740805.452097852305506.52731362740807.165496583
2305319.31207291740828.4683340612305287.78682353740984.698379446
#Sta/Elev= 30
       0 1982.21     9.4 1979.36    41.8  1962.2    48.1 1960.01    53.2 1959.23
    67.3 1958.84   108.8 1960.32   125.4 1959.84   129.9 1958.25   192.7  1956.7
   260.8 1957.24   276.9  1956.3   284.9 1954.83   328.9  1956.5   345.1  1959.3
     369  1959.6   411.3  1957.4   420.6 1955.75   427.5 1954.43   441.91955.736
   459.7 1957.07   552.3 1956.75   581.2 1957.74   594.3 1959.31   606.5 1958.36
   667.8 1958.48   708.6 1962.14   716.7 1964.35   737.1 1963.83   740.7  1964.8
#Mann= 8, -1 ,  0
       0     0.1       0      60    0.07       0  239.92    0.05       0
  339.92    0.06       0   420.6   0.045       0   441.9    0.06       0
  542.91    0.07       0  621.33    0.05       0
Bank Sta=420.6,441.9
XS Rating Curve= 0 ,0
Exp/Cntr(USF)=0,0
Exp/Cntr=0.3,0.1

Type RM Length L Ch R = 1 ,3959    ,270.8,270.8,270.8
BEGIN DESCRIPTION:
Structure XS 2
END DESCRIPTION:
XS GIS Cut Line= 5
2305589.89455292740467.1303624032305505.69405098740558.782780495
2305515.05941419740767.3774144272305304.34334033 740793.47080873
2305255.99275955740994.603222388
#Sta/Elev= 30
       0 1978.36    33.8 1961.11    40.8 1959.42    49.8 1958.85     109 1960.11
   114.9 1959.87   124.5 1956.63   166.9 1955.76     255 1957.04   266.9 1956.29
   282.4 1953.42   287.9 1953.74     295 1955.58   333.3 1957.24   348.3 1956.28
   387.7 1955.97   392.6 1955.11   398.4 1954.46  402.361955.119   408.7 1956.34
   525.6 1956.08   563.4 1958.07     582 1957.61   594.7 1959.22   614.8 1958.32
   668.7 1958.51   691.4 1960.71   724.6 1962.13   734.5 1964.03   752.5 1964.33
#Mann= 8, -1 ,  0
       0     0.1       0      50    0.07       0  234.46    0.05       0
  333.26    0.06       0   392.6   0.045       0  402.36    0.06       0
  493.26    0.07       0  615.59    0.05       0
Bank Sta=392.6,402.36
XS Rating Curve= 0 ,0
Exp/Cntr(USF)=0,0
Exp/Cntr=0.3,0.1

Type RM Length L Ch R = 1 ,3688    ,901.5,901.5,901.5
BEGIN DESCRIPTION:
Structure XS 1
END DESCRIPTION:
XS GIS Cut Line= 5
2305854.46107543740324.7429342362305489.69637009740437.315284289
2305503.64471107740624.6827572212305235.20614732740747.709418219
2305237.73935038740804.129943763
#Sta/Elev= 30
       0 2042.35    42.2 2026.26   102.9 2010.62   132.2 2007.82   169.8 2001.03
   228.4 1997.09   261.9 1991.96   287.1 1984.79   316.4 1973.29   320.5 1970.79
   328.9 1962.93   333.1 1960.68   366.6 1961.45   373.3 1960.17   381.7 1955.28
   453.8 1955.19   469.8 1951.87   493.9 1952.43   505.9 1954.94     518 1955.35
   621.8 1955.09632.59051953.434642.68771953.541   648.2  1954.9   665.8 1955.24
   747.6 1954.31   865.4 1955.81   906.4 1957.14   914.4 1959.74   921.4 1960.13
#Mann= 7, -1 ,  0
       0     0.1       0     310    0.06       0  411.74    0.07       0
  619.63    0.05       0632.5905   0.045       0642.6877    0.05       0
  729.63    0.07       0
Bank Sta=632.5905,642.6877
XS Rating Curve= 0 ,0
Exp/Cntr(USF)=0,0
Exp/Cntr=0.3,0.1

Type RM Length L Ch R = 1 ,2787    ,333.9,333.9,333.9
XS GIS Cut Line= 4
2305832.37752337740253.9949252892305593.65755352740261.066982339
 2305216.2599515740501.3738428052305216.57456189740806.895889315
#Sta/Elev= 30
       0 2055.72    48.2 2037.95    64.2 2029.99    72.2 2029.93    96.2 2020.65
   104.2 2019.91   120.3 2014.32   172.3 2002.35   238.8 1984.34   257.4 1980.63
     288 1976.42   292.7 1974.75   311.7 1963.41   354.4 1964.09   392.3 1957.63
   468.9 1952.96   553.6 1951.33     582 1953.19   593.4 1951.59     601 1950.52
  606.911951.462   629.4 1954.62   766.2 1954.69   778.2 1955.28   822.3 1954.26
   909.7 1956.14     942 1956.07     966 1956.88     982  1961.1   991.8 1960.98
#Mann= 6, -1 ,  0
       0     0.1       0  278.82    0.06       0  398.82    0.05       0
   593.4   0.045       0  606.91    0.05       0  856.24    0.07       0
#XS Ineff= 2 , 0
          584.84 1961.52  630.32         1968.55
Permanent Ineff=
       F       F
Bank Sta=593.4,606.91
XS Rating Curve= 0 ,0
Exp/Cntr(USF)=0,0
Exp/Cntr=0.3,0.1

Type RM Length L Ch R = 1 ,2453    ,299.1,299.1,299.1
BEGIN DESCRIPTION:
Structure
END DESCRIPTION:
XS GIS Cut Line= 2
2305829.58114315740243.9921154622305182.21252693740253.113823494
#Sta/Elev= 30
       0 2057.47    49.4 2039.58    61.4 2032.71    69.4 2032.86    81.4  2027.6
   109.4 2018.13   165.4  2004.2   221.4 1988.28   277.4 1974.16   289.4 1965.03
   293.4 1963.27   321.4 1964.15   325.4 1964.59   329.4 1966.01   333.4 1966.23
   361.4 1962.51   377.6 1962.23   389.7 1958.48   409.4 1954.21   441.5 1952.03
   465.5 1951.61   497.5 1949.53510.10061950.201   519.6 1950.21   577.5 1950.32
   585.5 1951.34   597.5 1951.46   621.5 1953.34   637.5 1955.96   647.4 1956.28
#Mann= 5, -1 ,  0
       0     0.1       0     270    0.06       0     370    0.05       0
510.1006   0.045       0   519.6    0.05       0
#XS Ineff= 2 , 0
          505.42 1958.83  525.63         1958.21
Permanent Ineff=
       F       F
Bank Sta=510.1006,519.6
XS Rating Curve= 0 ,0
Exp/Cntr(USF)=0,0
Exp/Cntr=0.3,0.1

Type RM Length L Ch R = 1 ,2154    ,1274.2,1274.2,1274.2
BEGIN DESCRIPTION:
Structure XS 4
END DESCRIPTION:
XS GIS Cut Line= 3
2305833.84615085740083.634136982 2305206.3606921740103.059367099
2305165.25358449740186.403042037
#Sta/Elev= 30
       0 2085.58    21.7 2079.88    49.7 2069.91    65.7 2061.72    73.7  2061.1
    77.7 2059.56    89.7 2052.18   129.7 2034.29   210.7 1994.82   232.1 1987.17
   265.8  1978.3   269.8 1976.18   289.8 1961.12   293.8  1960.2   329.8 1961.43
   333.8 1960.54   345.8 1954.72   353.8 1952.48   401.9 1951.31407.49941950.308
   413.9  1949.3   417.9 1950.28   426.2 1951.61   437.9 1949.09   537.9 1950.36
   557.9 1955.75   577.9 1951.68     614 1950.97   663.9 1955.43   720.7 1955.54
#Mann= 5, -1 ,  0
       0     0.1       0     180    0.06       0     380    0.05       0
407.4994   0.045       0   417.9    0.05       0
Bank Sta=407.4994,417.9
XS Rating Curve= 0 ,0
Exp/Cntr(USF)=0,0
Exp/Cntr=0.5,0.3

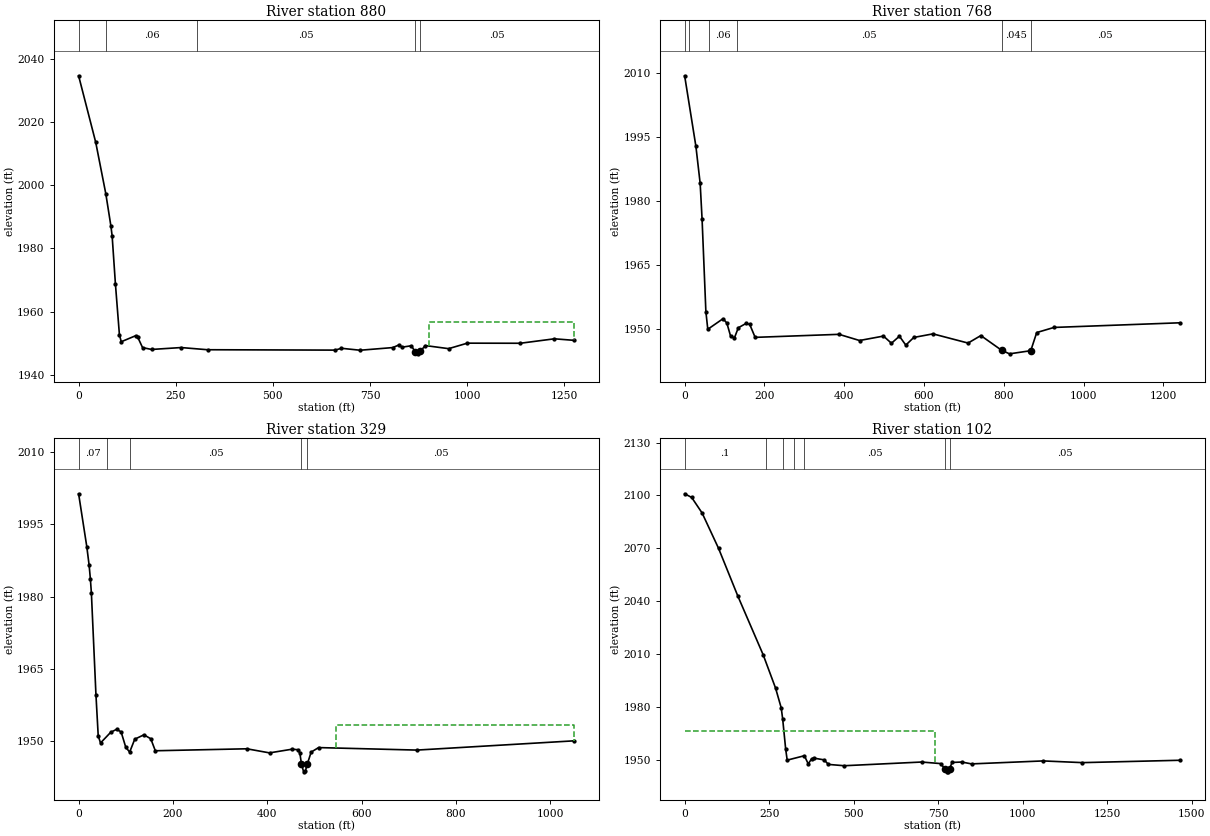
Type RM Length L Ch R = 1 ,880     ,111.5,111.5,111.5
BEGIN DESCRIPTION:
Structure XS 3 61.8ft
END DESCRIPTION:
XS GIS Cut Line= 4
2305317.88589871738864.7261354712305176.66001255738950.673000313
2305197.55641813739421.9678817892305215.75711856740058.992396721
#Sta/Elev= 30
       0 2034.65    44.1 2013.55    70.1 1997.24    83.1 1987.09    86.3 1983.96
    94.7 1968.79     105  1952.7   109.7 1950.45   147.2 1952.38   151.8 1951.98
   164.6 1948.59   187.9 1948.01   263.9 1948.61   331.9 1947.92   660.3  1947.8
   676.3 1948.38   724.5 1947.76   808.4  1948.6   824.4 1949.43   832.4 1948.73
   856.4 1949.18865.72741947.357   872.4 1946.62878.82741947.364   892.4 1949.24
   952.4 1948.26  1000.4    1950  1136.8 1949.97  1224.5 1951.38  1274.4  1950.9
#Mann= 5, -1 ,  0
       0     0.1       0      70    0.06       0  305.32    0.05       0
865.7274   0.045       0878.8274    0.05       0
#XS Ineff= 2 , 0
                          900.65         1956.72
Permanent Ineff=
       F       F
Bank Sta=865.7274,878.8274
XS Rating Curve= 0 ,0
Exp/Cntr(USF)=0,0
Exp/Cntr=0.5,0.3

Type RM Length L Ch R = 1 ,768     ,439.5,439.5,439.5
BEGIN DESCRIPTION:
Structure XS 2 24.3ft 8.1
END DESCRIPTION:
XS GIS Cut Line= 4
2305268.72430205738858.7608672822305120.82273498738955.425109042
2305118.29185817739382.696355093 2305136.4925586740019.720870025
#Sta/Elev= 30
       0 2009.46    28.2 1992.89    38.9 1984.19    43.7 1975.76    53.2 1954.09
      58 1949.93    96.2 1952.41   105.8 1951.39   115.3 1948.28   124.9 1947.93
   134.5 1950.28   153.6 1951.29   163.1 1951.08   176.7 1948.03     387 1948.74
   438.4 1947.29   498.4 1948.33   518.4 1946.65   538.4  1948.3   554.4 1946.21
   574.4 1948.01   622.5 1948.85   710.5 1946.69   742.5 1948.45794.50331945.003
   814.4 1944.16867.6833  1944.9   882.6 1949.16   925.9 1950.36  1241.3 1951.45
#Mann= 6, -1 ,  0
       0     0.1       0      10    0.07       0      60    0.06       0
     130    0.05       0794.5033   0.045       0867.6833    0.05       0
Bank Sta=794.5033,867.6833
XS Rating Curve= 0 ,0
Exp/Cntr(USF)=0,0
Exp/Cntr=0.5,0.3

Type RM Length L Ch R = 1 ,329     ,226.2,226.2,226.2
BEGIN DESCRIPTION:
Structure XS 1
END DESCRIPTION:
XS GIS Cut Line= 4
2305254.57406636738857.0425095372305072.54860914738981.266459425
2305046.93028178739287.6218060342304844.33557803739769.191597892
#Sta/Elev= 30
       0 2001.37    17.4 1990.35    22.3 1986.53    24.9 1983.73    27.1 1980.74
    36.8 1959.54    41.6 1951.05    46.5 1949.59      68  1951.8    80.4 1952.42
    90.1  1951.9   100.1 1948.67   108.3  1947.7   119.1 1950.38   138.5 1951.28
     153 1950.47   162.7 1947.97   356.8 1948.38   404.9 1947.53   453.1  1948.3
   465.2 1948.18   469.2 1947.52   472.5 1945.32   477.2 1943.59   481.2 1943.86
   485.2 1945.25   493.2 1947.69     509 1948.63   717.4 1948.11  1050.2 1950.03
#Mann= 5, -1 ,  0
       0    0.07       0      60    0.06       0     110    0.05       0
   472.5   0.045       0   485.2    0.05       0
#XS Ineff= 2 , 0
                          544.98         1953.28
Permanent Ineff=
       F       F
Bank Sta=472.5,485.2
XS Rating Curve= 0 ,0
Exp/Cntr(USF)=0,0
Exp/Cntr=0.3,0.1

Type RM Length L Ch R = 1 ,102     ,,,
XS GIS Cut Line= 4
2305475.02238167738911.8361682432305199.42808811738783.104623226
2304688.36851313739299.1761194242304736.41754984739731.036838067
#Sta/Elev= 30
       0 2100.94    20.8 2098.86    51.7 2090.01   100.3 2069.95   157.6 2042.74
   232.4 2009.46     269 1990.57   285.7 1979.37   290.1 1972.93   298.9  1955.9
   303.4 1949.67   354.3 1952.17   365.6 1947.54   375.8 1950.46   382.7  1950.8
   412.6 1949.82   425.3 1947.24     472 1946.49   701.2 1948.59   757.9  1947.7
  769.33 1944.75   774.9 1943.02   780.3 1943.15   783.7 1944.73   791.2 1948.35
   819.9 1948.59   848.8 1947.53  1060.7 1949.22    1177 1948.25    1465 1949.59
#Mann= 7, -1 ,  0
       0     0.1       0     240    0.07       0     290     0.1       0
  324.18    0.07       0  354.18    0.05       0  769.33   0.045       0
   783.7    0.05       0
#XS Ineff= 2 , 0
          740.51 1966.38
Permanent Ineff=
       F       F
Bank Sta=769.33,783.7
XS Rating Curve= 0 ,0
Exp/Cntr(USF)=0,0
Exp/Cntr=0.3,0.1
LCMann Table=0

Chan Stop Cuts=-1
Use User Specified Reach Order=0
Composite Channel Slope=5